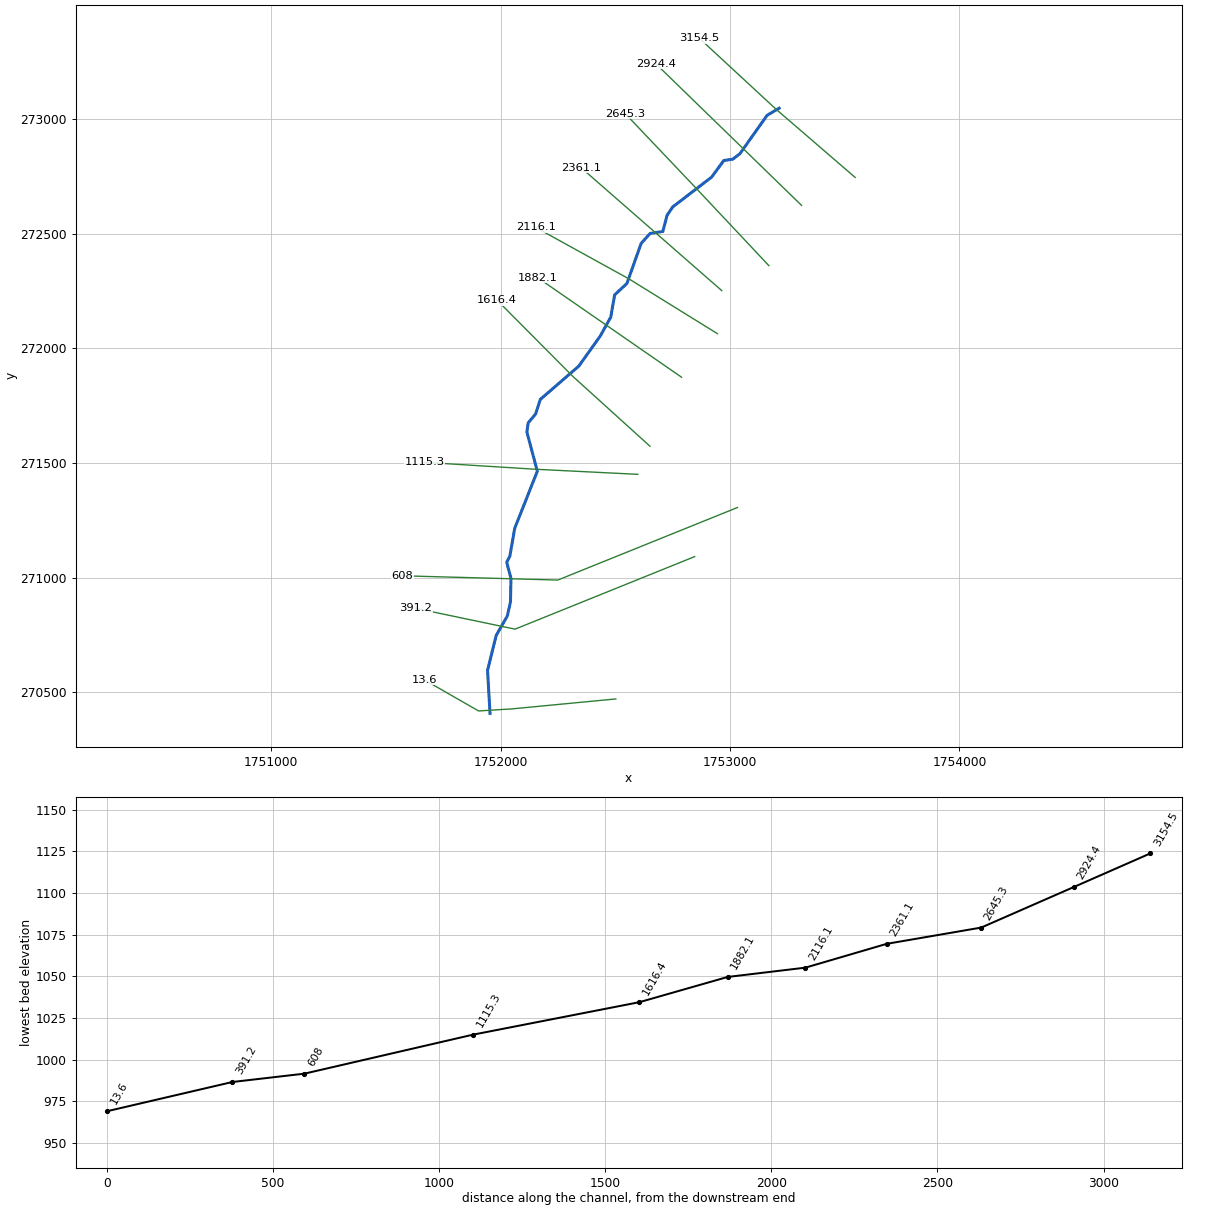
--- BeechBr.prj (project) ---

Proj Title=BeechBr
Current Plan=p01
Geom File=g01
Flow File=f01
Plan File=p01
DSS Export Rating Curves=0
DSS Export Rating Curve Sorted=0
DSS Export Volume Flow Curves=0
DXF OffsetX=0
DXF OffsetY=0
DXF ScaleX=0
DXF ScaleY=0

--- BeechBr.p01 (plan) ---

Plan Title=Floodplain
Program Version=4.00
Geom File=g01
Flow File=f01
K Sum by GR=0
Std Step Tol=0.01
Critical Tol=0.01
Num of Std Step Trials=20
Max Error Tol=0.3
Flow Tol Ratio=0.001
Split Flow NTrial=30
Split Flow Tol=0.02
Split Flow Ratio=0.02
Log Output Level=0
Friction Slope Method=1
Unsteady Friction Slope Method=2
Unsteady Bridges Friction Slope Method=1
Global Log Level=0
CheckData=False
Run HTab=0
Run UNet=0
Run PostProcess=0
UNET Theta=0
UNET Theta Warmup=0
UNET ZTol=0
UNET ZSATol=0
UNET MxIter=0
UNET MaxInSteps=0
UNET DtIC=0
UNET DtMin=0
UNET MaxCRTS=0
UNET WFStab=0
UNET SFStab=0
UNET WFX=0
UNET SFX=0
UNET DSS MLevel=0
UNET DZMax Abort=0
UNET Convert EG Bridges=0
UNET Use Existing IB Tables=0
UNET Froude Limit=0
UNET Froude Power=0
Write IC File=0
Echo Input=False
Echo Output=False
Write Detailed=0

--- BeechBr.f01 (steady flow) ---

Flow Title=NFF Regression Equation
Program Version=4.00
Number of Profiles=1
Profile Names=P100yr
River Rch & RM=BeechBr,Main      ,3154.5
700.7302
River Rch & RM=BeechBr,Main      ,2361.1
730.5599
River Rch & RM=BeechBr,Main      ,13.6
784.9761
Boundary for River Rch & Prof#=BeechBr,Main      ,1
Up Type=0
Dn Type=3
Dn Slope=0.038423

--- BeechBr.g01 (geometry) ---

Geom Title=USGS 10m DEM
Program Version=4.00

River Reach=BeechBr     ,Main
Reach XY= 30
     1753213.968      273046.536     1753161.339      273015.288
     1753042.653      272847.664     1753011.715      272824.320
     1752972.622      272818.414     1752919.747      272746.133
     1752749.873      272615.915     1752725.404      272579.634
     1752706.842      272509.041     1752651.389      272500.494
     1752612.389      272456.994     1752550.389      272282.495
     1752496.890      272232.495     1752479.890      272135.496
     1752433.890      272052.996     1752340.891      271922.497
     1752172.892      271776.998     1752152.392      271713.498
     1752119.892      271674.498     1752114.392      271634.999
     1752159.892      271463.999     1752061.392      271215.501
     1752039.892      271093.002     1752026.392      271067.502
     1752044.892      270997.002     1752042.892      270895.003
     1752028.892      270832.503     1751980.393      270748.003
     1751942.893      270596.004     1751953.666      270408.499

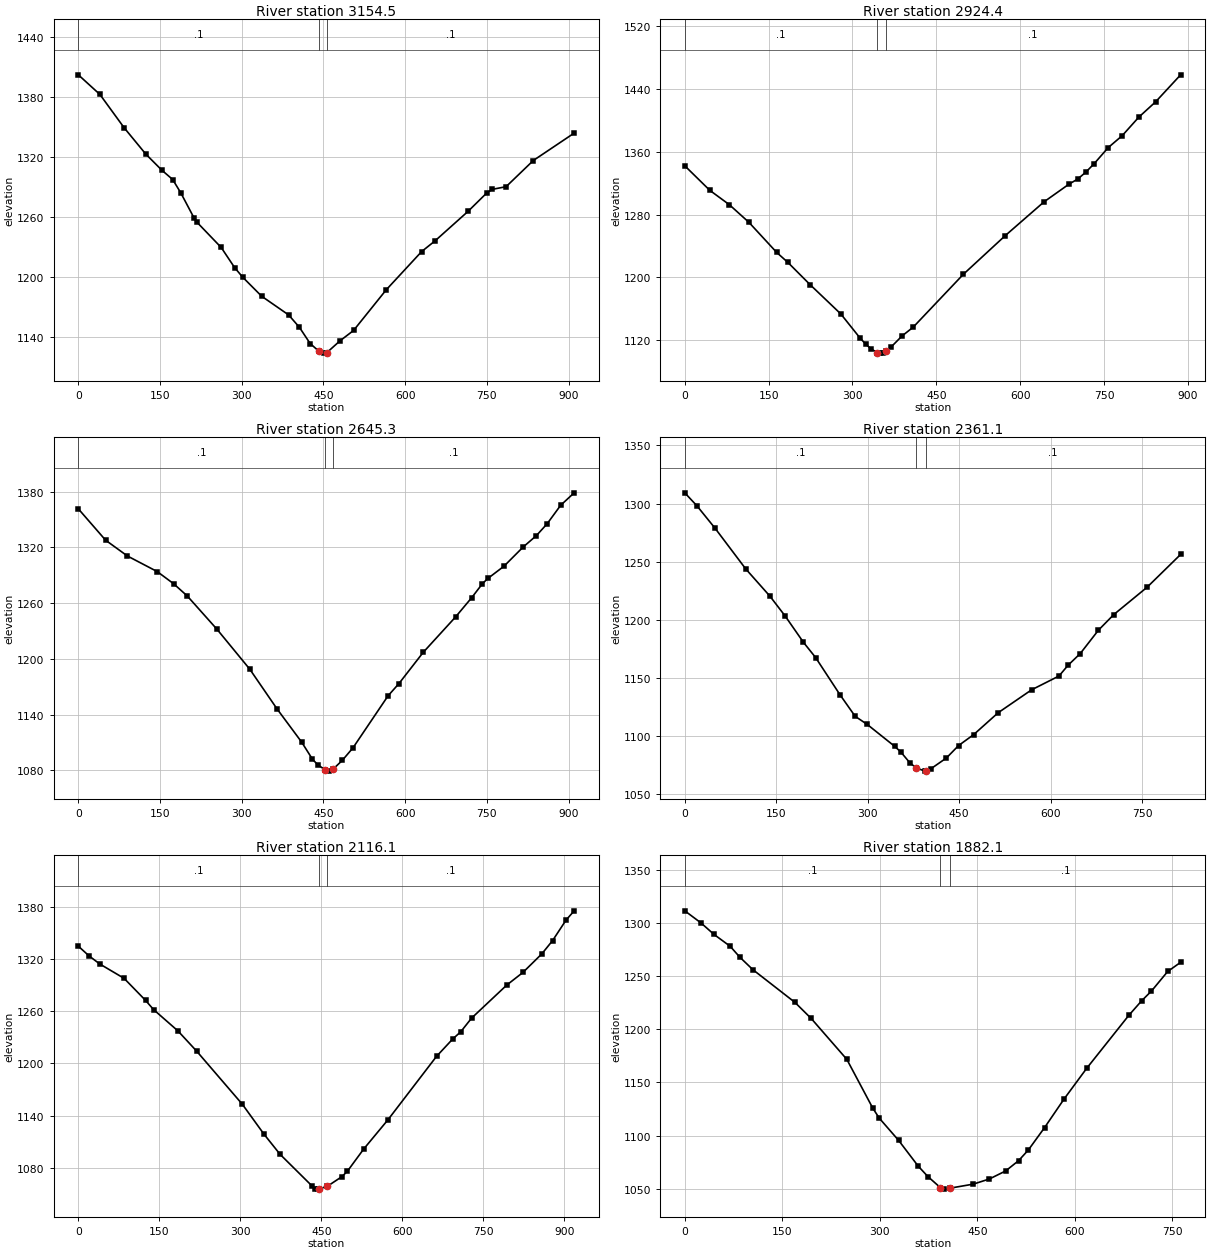
Type RM Length L Ch R = 1 ,3154.5,231.2,230.1,229.6
XS GIS Cut Line= 3
     1753545.295      272744.686     1753200.426      273042.009
     1752866.496      273350.976
#Sta/Elev= 30
       0 1402.22    39.6 1382.59    84.1 1349.26   123.7 1323.01   153.4 1306.78
   173.2 1297.50   188.1 1284.15   212.8 1258.66   217.8 1254.75   262.3 1229.49
   287.1 1209.23   301.9 1199.70   336.6 1180.71   386.0 1162.06   405.8 1149.68
   425.6 1133.42     441 1126.02   450.4 1123.80     456 1124.16   480.3 1136.06
   505.3 1146.47   565.3 1187.16   630.3 1225.41   655.3 1236.30   715.3 1265.54
   750.3 1284.28   760.3 1287.69   785.3 1290.30   835.3 1316.50   910.3 1343.91
#Mann= 3 , 0 , 0
       0     0.1       0     441   0.045       0     456     0.1       0
Bank Sta=     441,     456
Exp/Cntr=0.3,0.1

Type RM Length L Ch R = 1 ,2924.4,278.2,279.1,279
XS GIS Cut Line= 2
     1753311.748      272622.729     1752675.678      273240.965
#Sta/Elev= 30
       0 1342.08    44.8 1310.82    79.7 1292.59   114.6 1270.22   164.4 1231.82
   184.4 1219.13   224.2 1190.77   279.1 1153.53   313.9 1122.53   323.9 1114.93
   333.9 1108.66   344.7 1104.32   348.8 1103.66   353.8 1103.91   359.7 1106.16
   368.8 1111.27   388.7 1125.55   408.6 1136.71   498.3 1203.99   573.1 1253.11
   642.8 1296.31   687.7 1318.95   702.6 1325.08   717.6 1334.12   732.5 1344.95
   757.4 1365.22   782.4 1380.39   812.3 1404.09   842.2 1423.48   887.0 1457.89
#Mann= 3 , 0 , 0
       0     0.1       0   344.7   0.045       0   359.7     0.1       0
Bank Sta=   344.7,   359.7
Exp/Cntr=0.3,0.1

Type RM Length L Ch R = 1 ,2645.3,276.3,284.2,287.9
XS GIS Cut Line= 3
     1753169.211      272360.128     1752857.789      272691.493
     1752544.162      273021.684
#Sta/Elev= 30
       0 1361.55    50.0 1327.84    90.0 1310.84   144.9 1294.00   174.9 1280.96
   199.9 1267.82   254.8 1231.74   314.8 1188.91   364.8 1146.20   409.8 1110.62
   429.8 1092.06   439.8 1085.97   452.2 1081.05   459.7 1079.30   467.2 1081.21
   484.4 1090.80   504.2 1104.43   568.6 1160.41   588.4 1173.47   632.9 1207.02
   692.3 1245.14   722.0 1265.94   741.8 1281.07   751.7 1286.66   781.4 1299.87
   816.1 1320.26   840.8 1332.77   860.6 1345.56   885.4 1365.43   910.1 1378.79
#Mann= 3 , 0 , 0
       0     0.1       0   452.2   0.045       0   467.2     0.1       0
Bank Sta=   452.2,   467.2
Exp/Cntr=0.3,0.1

Type RM Length L Ch R = 1 ,2361.1,247.9,245,247.3
XS GIS Cut Line= 2
     1752963.990      272251.192     1752351.698      272786.205
#Sta/Elev= 30
       0 1309.20    20.0 1297.94    49.9 1278.52    99.8 1243.76   139.7 1220.14
   164.6 1203.10   194.6 1180.45   214.5 1167.38   254.4 1135.40   279.4 1116.75
   299.3 1109.72   344.2 1090.90   354.2 1086.06   369.1 1076.71   379.8 1072.21
   394.1 1069.56   394.8 1069.66   404.1 1071.78   429.0 1080.87   449.0 1091.60
   473.9 1101.08   513.8 1119.81   568.7 1139.57   613.6 1151.46   628.5 1160.72
   648.5 1170.80   678.4 1190.98   703.4 1204.32   758.2 1227.95   813.1 1256.14
#Mann= 3 , 0 , 0
       0     0.1       0   379.8   0.045       0   394.8     0.1       0
Bank Sta=   379.8,   394.8
Exp/Cntr=0.3,0.1

Type RM Length L Ch R = 1 ,2116.1,235.2,233.9,231.7
XS GIS Cut Line= 3
     1752945.034      272063.588     1752559.620      272302.175
     1752152.716      272526.646
#Sta/Elev= 30
       0 1335.12    19.9 1323.90    39.8 1314.57    84.7 1298.08   124.5 1272.64
   139.5 1261.97   184.3 1237.58   219.2 1214.12   303.8 1152.90   343.7 1118.58
   373.6 1095.30   433.4 1058.46   438.3 1055.90   443.3 1055.26   445.9 1055.62
   460.9 1058.46   488.3 1069.78   498.3 1076.01   528.2 1101.34   573.2 1135.10
   663.2 1208.20   693.1 1228.16   708.1 1236.58   728.1 1252.25   793.1 1290.26
   823.1 1304.85   858.0 1326.17   878.0 1341.51   903.0 1365.20   918.0 1375.85
#Mann= 3 , 0 , 0
       0     0.1       0   445.9   0.045       0   460.9     0.1       0
Bank Sta=   445.9,   460.9
Exp/Cntr=0.3,0.1

Type RM Length L Ch R = 1 ,1882.1,269.4,265.8,261.7
XS GIS Cut Line= 2
     1752788.625      271873.711     1752161.472      272307.666
#Sta/Elev= 30
       0 1311.21    24.9 1299.84    44.9 1289.05    69.8 1277.88    84.7 1267.61
   104.7 1255.92   169.5 1225.12   194.4 1210.06   249.2 1171.63   289.1 1125.82
   299.1 1116.37   329.0 1095.38   358.9 1071.36   373.8 1061.54   393.1 1051.10
   398.8 1049.68   408.1 1050.61   443.6 1054.36   468.6 1059.25   493.5 1066.77
   513.4 1076.44   528.4 1086.47   553.3 1107.47   583.2 1134.25   618.1 1163.19
   682.9 1212.97   702.8 1226.76   717.8 1235.86   742.7 1254.20   762.6 1262.82
#Mann= 3 , 0 , 0
       0     0.1       0   393.1   0.045       0   408.1     0.1       0
Bank Sta=   393.1,   408.1
Exp/Cntr=0.3,0.1

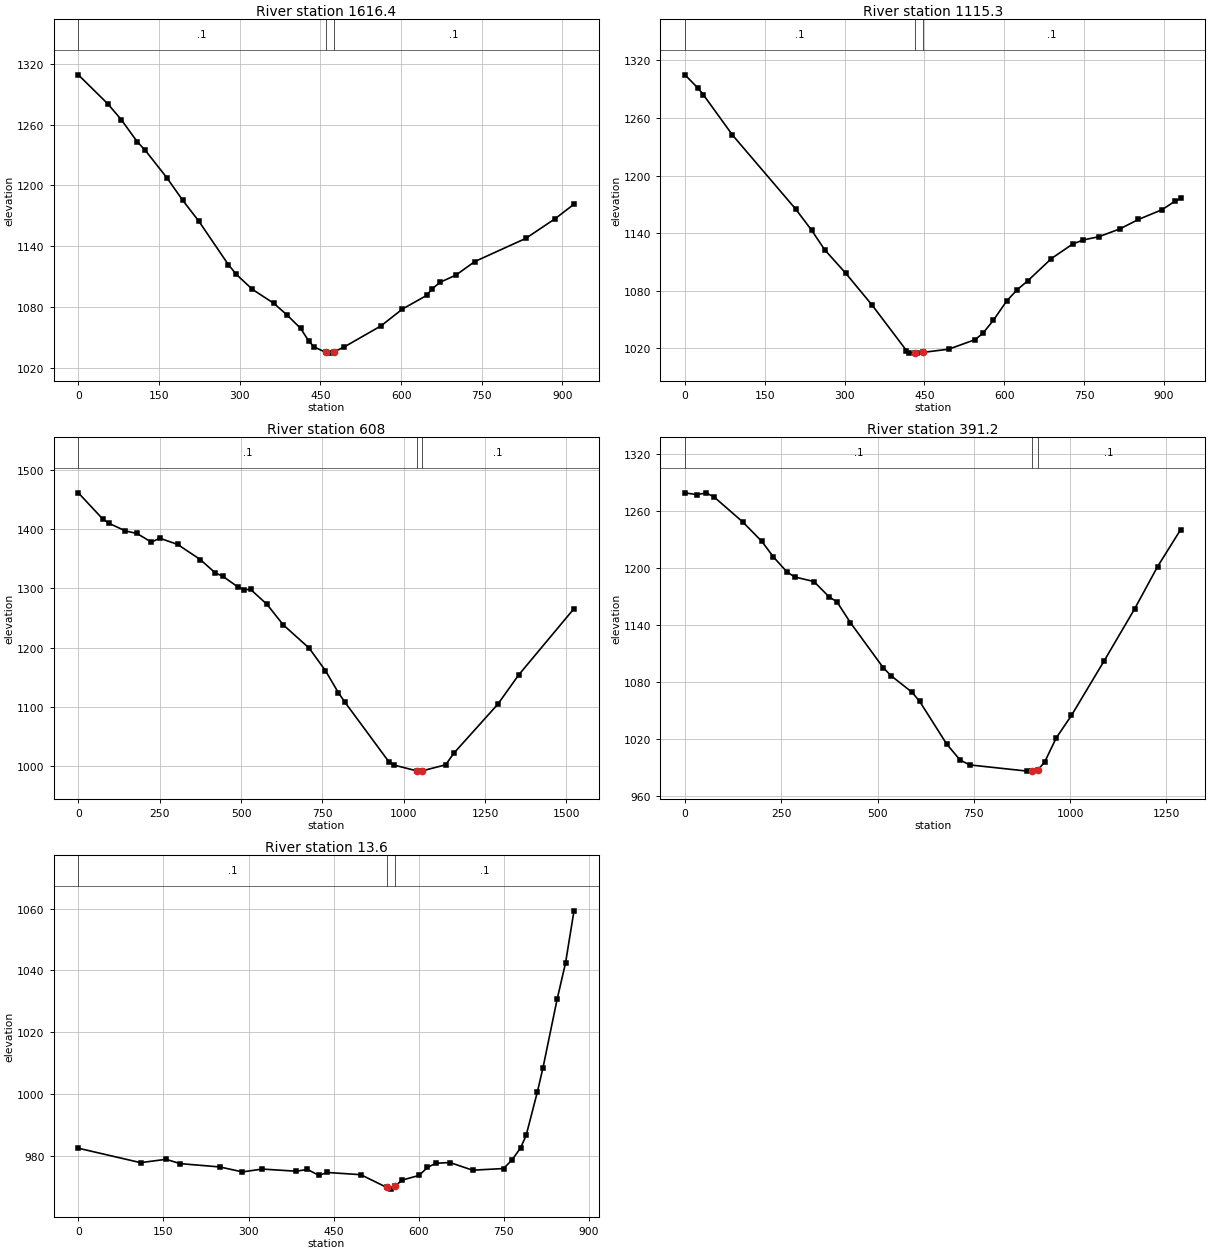
Type RM Length L Ch R = 1 ,1616.4,484.5,501.1,517.9
XS GIS Cut Line= 3
     1752650.800      271573.060     1752314.948      271877.211
     1751984.683      272209.275
#Sta/Elev= 30
       0 1309.21    54.8 1280.58    79.7 1265.05   109.5 1243.18   124.5 1234.63
   164.3 1207.83   194.2 1185.29   224.1 1164.69   278.8 1121.97   293.8 1112.21
   323.6 1097.49   363.5 1083.64   388.4 1071.99   413.3 1058.92   428.2 1046.57
   438.2 1040.68   459.5 1035.40   468.0 1034.55   474.5 1035.70   493.0 1040.27
   562.7 1061.46   602.6 1078.09   647.4 1091.46   657.4 1097.82   672.3 1104.39
   702.2 1111.66   737.1 1124.96   831.8 1147.79   886.6 1167.32   921.4 1181.51
#Mann= 3 , 0 , 0
       0     0.1       0   459.5   0.045       0   474.5     0.1       0
Bank Sta=   459.5,   474.5
Exp/Cntr=0.3,0.1

Type RM Length L Ch R = 1 ,1115.3,507,507.3,507.6
XS GIS Cut Line= 3
     1752597.853      271450.447     1752147.683      271472.873
     1751668.114      271502.845
#Sta/Elev= 30
       0 1304.85    24.8 1290.78    34.7 1284.01    89.2 1242.20   208.0 1165.05
   237.8 1143.14   262.5 1122.68   302.1 1098.19   351.7 1064.97   416.1 1017.77
   421.0 1015.66   431.4 1015.07   435.9 1015.05   446.4 1015.77   495.3 1019.14
   544.8 1029.02   559.7 1035.67   579.5 1049.32   604.3 1069.26   624.1 1081.10
   643.9 1090.27   688.5 1113.57   728.1 1128.52   748.0 1132.88   777.7 1136.28
   817.3 1144.48   852.0 1154.25   896.6 1164.49   921.3 1173.51   931.2 1176.08
#Mann= 3 , 0 , 0
       0     0.1       0   431.4   0.045       0   446.4     0.1       0
Bank Sta=   431.4,   446.4
Exp/Cntr=0.3,0.1

Type RM Length L Ch R = 1 ,608,220.4,216.8,213
XS GIS Cut Line= 3
     1753032.214      271305.866     1752249.301      270989.689
     1751570.647      271008.219
#Sta/Elev= 30
       0 1461.02    74.9 1416.98    94.9 1409.38   144.9 1396.72   179.9 1392.54
   224.8 1377.82   249.8 1384.51   304.8 1374.10   374.7 1348.55   419.7 1326.49
   444.7 1319.99   489.6 1302.60   509.6 1297.65   529.6 1298.03   579.6 1273.03
   629.5 1238.48   709.4 1199.08   759.4 1161.09   799.4 1123.70   819.4 1107.85
   954.2 1007.50   969.2 1002.01  1041.4  991.90  1049.0  991.66  1056.4  992.07
  1128.9 1002.33  1153.8 1021.80  1288.6 1104.19  1353.5 1154.08  1523.2 1265.70
#Mann= 3 , 0 , 0
       0     0.1       0  1041.4   0.045       0  1056.4     0.1       0
Bank Sta=  1041.4,  1056.4
Exp/Cntr=0.3,0.1

Type RM Length L Ch R = 1 ,391.2,371.7,377.5,383.7
XS GIS Cut Line= 3
     1752845.730      271091.853     1752062.817      270775.677
     1751629.403      270866.431
#Sta/Elev= 30
       0 1279.18    30.0 1277.30    55.0 1278.98    74.9 1275.09   149.9 1248.63
   199.8 1228.04   229.8 1211.74   264.8 1196.03   284.8 1190.78   334.7 1185.96
   374.7 1169.71   394.7 1164.59   429.7 1142.69   514.6 1095.55   534.6 1087.13
   589.5 1069.65   609.5 1059.97   679.5 1015.21   714.4  998.36   739.4  993.20
   889.1  986.66   900.5  986.77   915.5  987.57   933.9  996.07   963.8 1021.29
  1003.6 1045.15  1088.1 1102.24  1167.8 1157.24  1227.4 1201.72  1287.2 1240.45
#Mann= 3 , 0 , 0
       0     0.1       0   900.5   0.045       0   915.5     0.1       0
Bank Sta=   900.5,   915.5
Exp/Cntr=0.3,0.1

Type RM Length L Ch R = 1 ,13.6,14.7,13.6,12.6
XS GIS Cut Line= 4
     1752502.129      270471.474     1752050.320      270428.146
     1751903.840      270419.054     1751666.898      270555.032
#Sta/Elev= 30
       0  982.38   109.7  977.70   154.6  978.78   179.6  977.38   249.4  976.31
   289.3  974.70   324.2  975.62   384.0  974.93   404.0  975.50   424.0  973.58
   438.9  974.52   497.9  973.80   543.4  969.71   551.7  969.12   558.4  970.17
   571.3  972.08   600.6  973.55   615.5  976.16   630.4  977.52   655.3  977.73
   695.0  975.26   749.6  975.79   764.6  978.59   779.5  982.45   789.4  986.51
   809.3 1000.67   819.2 1008.51   844.0 1030.61   858.9 1042.43   873.8 1059.32
#Mann= 3 , 0 , 0
       0     0.1       0   543.4   0.045       0   558.4     0.1       0
Bank Sta=   543.4,   558.4
Exp/Cntr=0.3,0.1